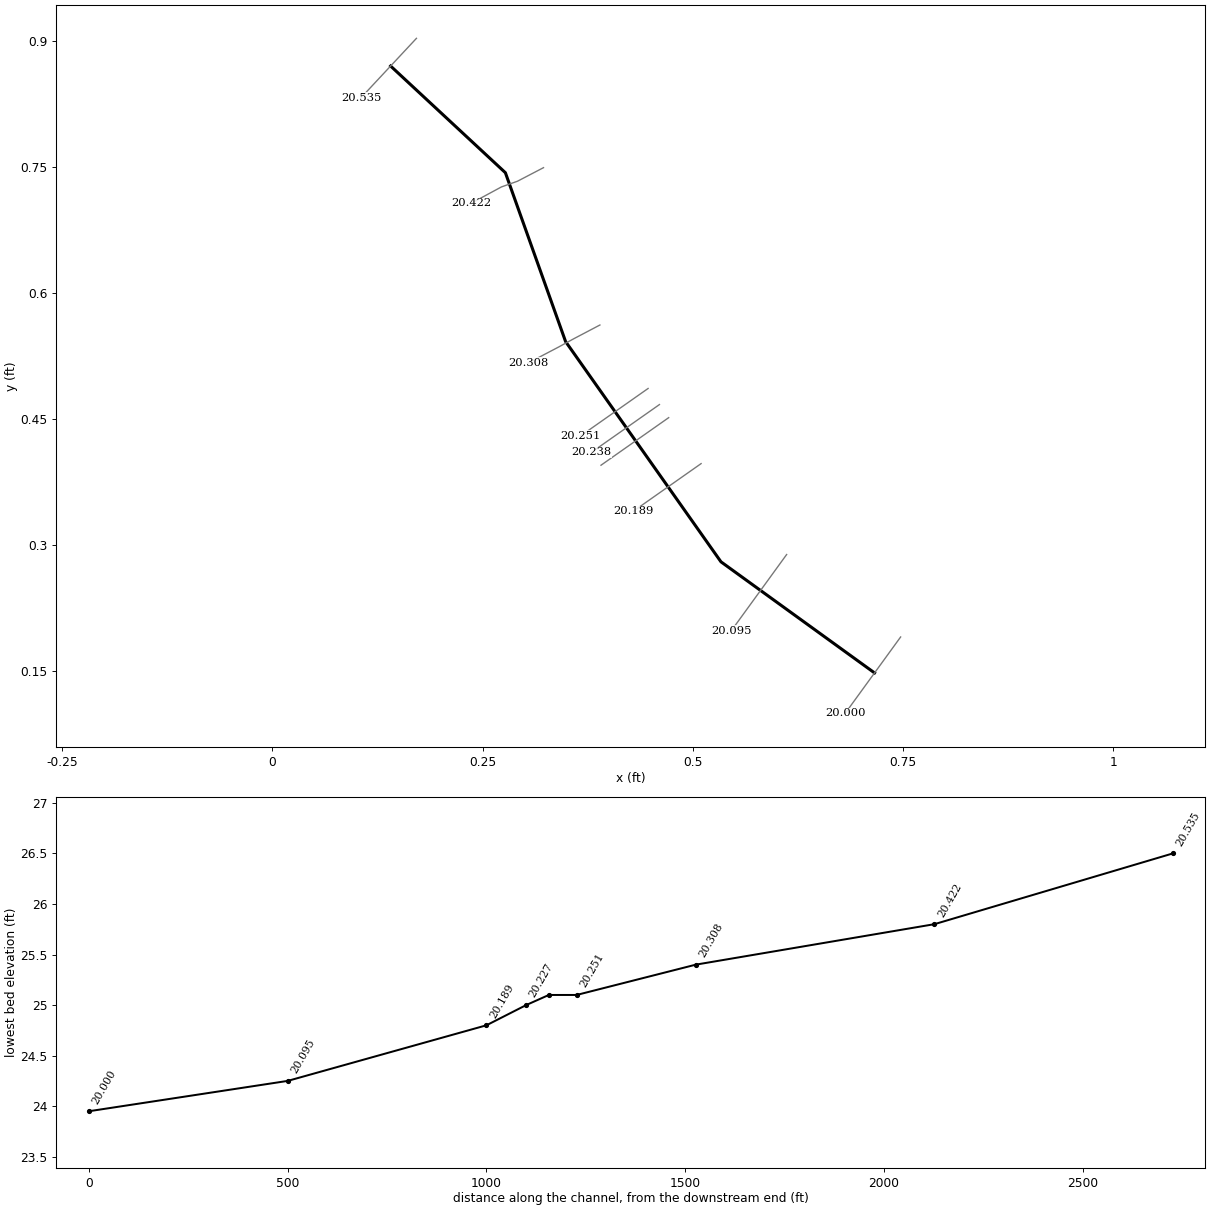
--- TWINPIPE.prj (project) ---

Proj Title=Twin Circular Pipe - Example 3
Current Plan=p01
Default Exp/Contr=0.3,0.1
English Units
Geom File=g01
Geom File=g02
Flow File=f01
Plan File=p01
Plan File=p02
Y Axis Title=Elevation
X Axis Title(PF)=Main Channel Distance
X Axis Title(XS)=Station
BEGIN DESCRIPTION:
END DESCRIPTION:
DSS Export Rating Curves= 0
DSS Export Rating Curve Sorted= 0
DSS Export Volume Flow Curves= 0
DXF OffsetX= 0
DXF OffsetY= 0
DXF ScaleX= 1
DXF ScaleY= 10

--- TWINPIPE.p01 (plan) ---

Plan Title=Spring Creek Culverts
Version=Version 3.0.2  Apr 2001
Short Identifier=Base Plan
Geom File=g01
Flow File=f01
Subcritical Flow
K Sum by GR=-1
Std Step Tol= 0.01
Critical Tol= 0.01
Num of Std Step Trials= 20
Max Error Tol= 0.3
Flow Tol Ratio= 0.001
Split Flow NTrial= 30
Split Flow Tol= 0.02
Split Flow Ratio= 0.02
Log Output Level= 0
Friction Slope Method= 1
Unsteady Friction Slope Method= 2
Calc Critical at every XS
Parabolic Critical Depth
Global Vel Dist= 0 , 0 , 0
Global Log Level= 0
Log Level Location=Spring Creek    ,Culvrt Reach    ,20.237  , 3 , 4
CheckData=True
Encroach Param=-1 ,0,0, 0
Computation Interval=1HOUR
Output Interval=1HOUR
Run HTab= 0
Run UNet= 0
Run PostProcess= 0
UNET Theta= 1
UNET ZTol= 0.02
UNET ZSATol= 0.1
UNET MxIter= 20
UNET MaxInSteps= 20
UNET DtIC= 0
UNET DtMin= 0
UNET MaxCRTS= 20
UNET WFStab= 2
UNET SFStab= 1
UNET WFX= 1
UNET SFX= 1
UNET Convert EG Bridges=-1
UNET Use Existing IB Tables=-1
Instantaneous Interval=1HOUR
Write IC File= 0
Write Velocity= 0
Write Detailed= 0

--- TWINPIPE.P02 (plan) ---

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Plan Title=Sp. Cr. Culverts - Adj. Weir Flow
Short Identifier=Adj.
Geom File=g02
Flow File=f01
Interactive Comp Mode

--- TWINPIPE.F01 (steady flow) ---

Flow Title=Multiple Pipe Flow Data
Number of Profiles= 3
Profile Names=5 yr        ,10 yr       ,25 yr
River Rch & RM=Spring Creek,Culvrt Reach,20.535
     250     400     600
Boundary for River Rch & Prof#=Spring Creek,Culvrt Reach, 1
Up Type= 0
Dn Type= 1
Dn Known WS=29.8
Boundary for River Rch & Prof#=Spring Creek,Culvrt Reach, 2
Up Type= 0
Dn Type= 1
Dn Known WS=31.2
Boundary for River Rch & Prof#=Spring Creek,Culvrt Reach, 3
Up Type= 0
Dn Type= 1
Dn Known WS=31.9

--- TWINPIPE.g01 (geometry) ---

Geom Title=Multiple Pipe Geometry
Program Version=5.00

River Reach=Spring Creek    ,Culvrt Reach
Reach XY= 5
        0.140665       0.8705235       0.2771363       0.7434402
       0.3487298       0.5422741       0.5334873       0.2798834
       0.7161126        0.147541

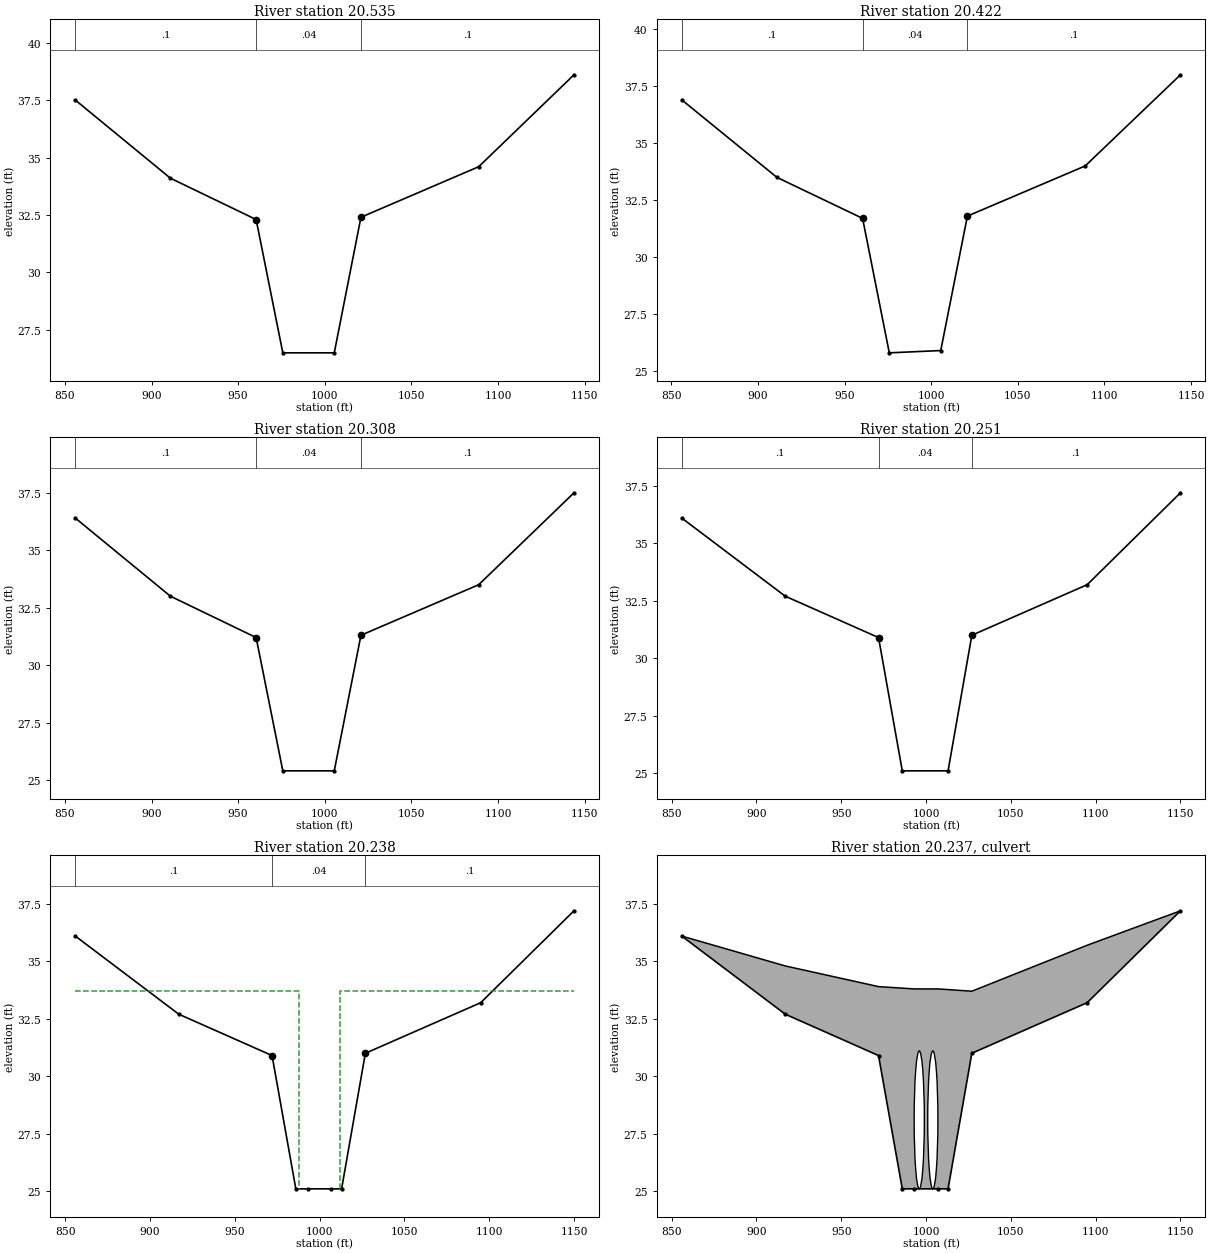
Type RM Length L Ch R = 1 ,20.535  ,650,600,500
BEGIN DESCRIPTION:
River mile 20.535 - Upstream Cross Section
END DESCRIPTION:
XS GIS Cut Line= 5
 0.1713861384587 0.90351409516820.147566702709820.87793505085698
        0.140665       0.87052350.133763297290180.86311194914302
0.105700175527950.83297572582375
#Sta/Elev= 8
     856    37.5   910.9    34.1   960.4    32.3   975.8    26.5  1005.5    26.5
  1020.9    32.4  1088.9    34.6  1143.9    38.6
#Mann= 3 , 0 , 0
     856      .1       0   960.4     .04       0  1020.9      .1       0
Bank Sta=960.4,1020.9
XS Rating Curve= 0 ,0
Exp/Cntr=0.3,0.1

Type RM Length L Ch R = 1 ,20.422  ,650,600,500
BEGIN DESCRIPTION:
River mile 20.422
END DESCRIPTION:
XS GIS Cut Line= 5
0.322486837236720.749451788238090.29150399325432 0.7332741368006
 0.2819628067602 0.72987850038240.27242162026607 0.7264828639642
0.23621041667911 0.7068747153067
#Sta/Elev= 8
     856    36.9   910.9    33.5   960.4    31.7   975.8    25.8  1005.5    25.9
  1020.9    31.8  1088.9      34  1143.9      38
#Mann= 3 , 0 , 0
     856      .1       0   960.4     .04       0  1020.9      .1       0
Bank Sta=960.4,1020.9
XS Rating Curve= 0 ,0
Exp/Cntr=0.3,0.1

Type RM Length L Ch R = 1 ,20.308  ,300,300,350
BEGIN DESCRIPTION:
River mile 20.308
END DESCRIPTION:
XS GIS Cut Line= 5
0.389544270081840.561995039481690.358615124932560.54571495939574
0.349733395411360.540848804125660.340851665890160.53598264885558
0.304392420092410.51683965653854
#Sta/Elev= 8
     856    36.4   910.9      33   960.4    31.2   975.8    25.4  1005.5    25.4
  1020.9    31.3  1088.9    33.5  1143.9    37.5
#Mann= 3 , 0 , 0
     856      .1       0   960.4     .04       0  1020.9      .1       0
Bank Sta=960.4,1020.9
XS Rating Curve= 0 ,0
Exp/Cntr=0.3,0.1

Type RM Length L Ch R = 1 ,20.251  ,70,70,70
BEGIN DESCRIPTION:
River mile 20.251
END DESCRIPTION:
XS GIS Cut Line= 5
0.446839348727030.486386498480940.415085641434440.46402771985384
0.407557822895250.458727147334480.400030004356050.45342657481513
0.366360125071670.42971855954673
#Sta/Elev= 8
     856    36.1     917    32.7     972    30.9     986    25.1    1013    25.1
    1027      31    1095    33.2    1150    37.2
#Mann= 3 , 0 , 0
     856      .1       0     972     .04       0    1027      .1       0
Bank Sta=972,1027
XS Rating Curve= 0 ,0
Exp/Cntr=0.3,0.1

Type RM Length L Ch R = 1 ,20.238  ,57,57,57
BEGIN DESCRIPTION:
River mile 20.238 - Upstream end of culvert
END DESCRIPTION:
XS GIS Cut Line= 5
0.46033171513993  0.4672247785630.42857800784734 0.4448659999359
0.421050189308150.439565427416540.413522370768960.43426485489718
0.379852491484580.41055683962879
#Sta/Elev= 10
     856    36.1     917    32.7     972    30.9     986    25.1     993    25.1
    1007    25.1    1013    25.1    1027      31    1095    33.2    1150    37.2
#Mann= 3 , 1 , 0
     856      .1       0     972     .04       0    1027      .1       0
#XS Ineff= 2 , 0
             988    33.7    1012            33.7
Permanent Ineff=
       F       F
Bank Sta=972,1027
XS Rating Curve= 0 ,0
Exp/Cntr=0.5,0.3

Type RM Length L Ch R = 2 ,20.237  ,,,
BEGIN DESCRIPTION:
Twin Circular Pipe Crossing
END DESCRIPTION:
Bridge Culvert-0,0,1,-1, 0
Deck Dist Width WeirC Skew NumUp NumDn MinLoCord MaxHiCord MaxSubmerge Is_Ogee
10,40,2.6,0, 8, 8, 33.7, , 0.95, 0, 2,2,,
     856     917     972     993    1007    1027    1095    1150
    36.1    34.8    33.9    33.8    33.8    33.7    35.7    37.2
                                                                
     856     917     972     993    1007    1027    1095    1150
    36.1    34.8    33.9    33.8    33.8    33.7    35.7    37.2
                                                                
Multiple Barrel Culv=1,6,,50,0.013,0.5,1,1,1,25.1,25, 2,Circular    , 0 ,5
     996     996    1004    1004
Culvert Bottom n=0.013
BC Design=,, 0 ,, 0 ,,,,,,
BC HTab HWMax=37.2
BC Use User HTab Curves=0
BC User HTab FreeFlow(D)= 0

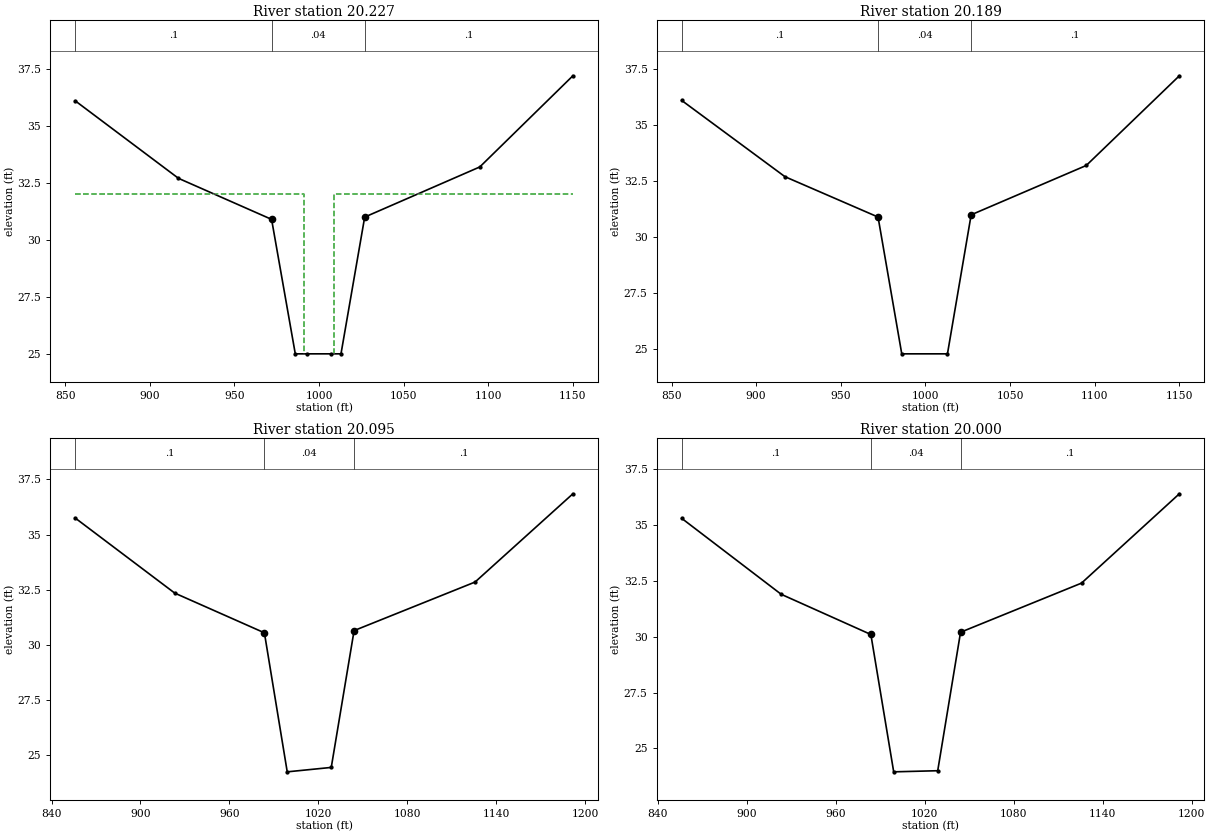
Type RM Length L Ch R = 1 ,20.227  ,100,100,100
BEGIN DESCRIPTION:
River mile 20.227 - Downstream end of culvert
END DESCRIPTION:
XS GIS Cut Line= 5
0.471318356361870.451621663772680.439564649069280.42926288514557
0.432036830530090.42396231262622 0.42450901199090.41866174010686
0.390839132706520.39495372483847
#Sta/Elev= 10
     856    36.1     917    32.7     972    30.9     986      25     993      25
    1007      25    1013      25    1027      31    1095    33.2    1150    37.2
#Mann= 3 , 1 , 0
     856      .1       0     972     .04       0    1027      .1       0
#XS Ineff= 2 , 0
       0     991      32    1009       0      32
Permanent Ineff=
       F       F
Bank Sta=972,1027
XS Rating Curve= 0 ,0
Exp/Cntr=0.5,0.3

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
Type RM Length L Ch R = 1 ,20.189  ,600,500,550
BEGIN DESCRIPTION:
River mile 20.189
END DESCRIPTION:
XS GIS Cut Line= 5
0.509867974684460.396873892578560.478114267391870.37451511395145
0.47058644885268 0.36921454143210.463058630313490.36391396891274
0.429388751029110.34020595364435
#Sta/Elev= 8
     856    36.1     917    32.7     972    30.9     986    24.8    1013    24.8
    1027      31    1095    33.2    1150    37.2
#Mann= 3 , 0 , 0
     856      .1       0     972     .04       0    1027      .1       0
Bank Sta=972,1027
XS Rating Curve= 0 ,0
Exp/Cntr=0.3,0.1

Type RM Length L Ch R = 1 ,20.095  ,500,500,450
BEGIN DESCRIPTION:
River mile 20.095
END DESCRIPTION:
XS GIS Cut Line= 5
0.611576036902960.288559004123190.586508771456330.25396754384764
0.580566099631520.245766980575340.574623427806710.23756641730305
0.545627123137060.19755309701275
#Sta/Elev= 8
     856   35.75   923.1   32.35   983.6   30.55     999   24.25  1028.7   24.45
  1044.1   30.65  1125.7   32.85  1191.7   36.85
#Mann= 3 , 0 , 0
     856      .1       0   983.6     .04       0  1044.1      .1       0
Bank Sta=983.6,1044.1
XS Rating Curve= 0 ,0
Exp/Cntr=0.3,0.1

Type RM Length L Ch R = 1 ,20.000  ,0,0,0
BEGIN DESCRIPTION:
River mile 20.000 - Downstream Cross Section
END DESCRIPTION:
XS GIS Cut Line= 5
0.747122537271450.190333023547850.722055271824810.15574156327229
       0.7161126        0.1475410.710169928175190.13934043672771
0.681173623505540.09932711643741
#Sta/Elev= 8
     856    35.3   923.1    31.9   983.6    30.1     999   23.95  1028.7      24
  1044.1    30.2  1125.7    32.4  1191.7    36.4
#Mann= 3 , 0 , 0
     856      .1       0   983.6     .04       0  1044.1      .1       0
Bank Sta=983.6,1044.1
XS Rating Curve= 0 ,0
Exp/Cntr=0.3,0.1

Chan Stop Cuts=-1
Use User Specified Reach Order=0
User Specified Reach Order=Spring Creek    ,Culvrt Reach
Composite Channel Slope=5

--- TWINPIPE.g02 (geometry) ---

Geom Title=Adjusted Ineffective + n Values
Program Version=4.01

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
River Reach=Spring Creek    ,Culvrt Reach
Reach XY= 5
        0.140665       0.8705235       0.2748268       0.7259475
        0.334873       0.5860058       0.5727483       0.2623907
       0.7413395       0.1720117

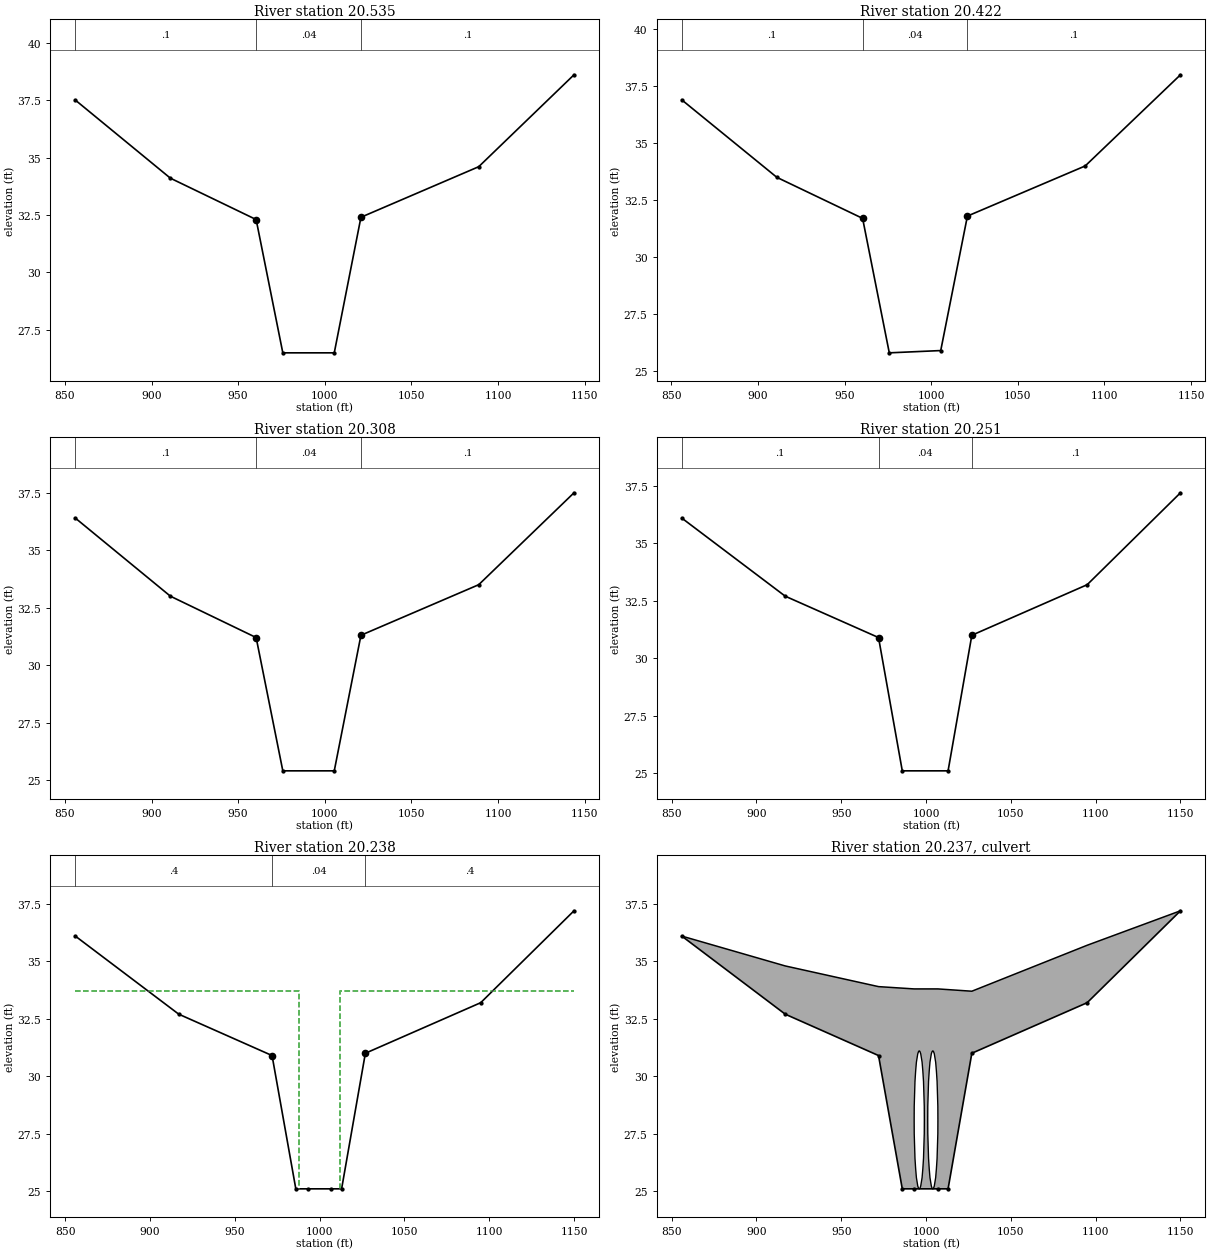
Type RM Length L Ch R = 1 ,20.535  ,650,600,500
BEGIN DESCRIPTION:
River mile 20.535 - Upstream Cross Section
END DESCRIPTION:
XS GIS Cut Line= 5
0.173568838374960.901057185973420.148057060381520.87738309029503
        0.140665       0.87052350.133272939618480.86366390970497
0.103215966827490.83577202189378
#Sta/Elev= 8
     856    37.5   910.9    34.1   960.4    32.3   975.8    26.5  1005.5    26.5
  1020.9    32.4  1088.9    34.6  1143.9    38.6
#Mann= 3 , 0 , 0
     856      .1       0   960.4     .04       0  1020.9      .1       0
Bank Sta=960.4,1020.9
XS Rating Curve= 0 ,0
Exp/Cntr=0.3,0.1

Type RM Length L Ch R = 1 ,20.422  ,650,600,500
BEGIN DESCRIPTION:
River mile 20.422
END DESCRIPTION:
XS GIS Cut Line= 5
0.314068071960530.747044700541230.284632640812060.72847405123434
0.275926005784720.723385727129060.267219370757370.71829740302378
 0.23258563477160.69634556139948
#Sta/Elev= 8
     856    36.9   910.9    33.5   960.4    31.7   975.8    25.8  1005.5    25.9
  1020.9    31.8  1088.9      34  1143.9      38
#Mann= 3 , 0 , 0
     856      .1       0   960.4     .04       0  1020.9      .1       0
Bank Sta=960.4,1020.9
XS Rating Curve= 0 ,0
Exp/Cntr=0.3,0.1

Type RM Length L Ch R = 1 ,20.308  ,300,300,350
BEGIN DESCRIPTION:
River mile 20.308
END DESCRIPTION:
XS GIS Cut Line= 5
 0.40096875152430.571877430594610.372925745843590.55126424416048
0.364800259986650.54529155504348 0.35667477412970.53931886592648
 0.32363560849650.51503322092182
#Sta/Elev= 8
     856    36.4   910.9      33   960.4    31.2   975.8    25.4  1005.5    25.4
  1020.9    31.3  1088.9    33.5  1143.9    37.5
#Mann= 3 , 0 , 0
     856      .1       0   960.4     .04       0  1020.9      .1       0
Bank Sta=960.4,1020.9
XS Rating Curve= 0 ,0
Exp/Cntr=0.3,0.1

Type RM Length L Ch R = 1 ,20.251  ,70,70,70
BEGIN DESCRIPTION:
River mile 20.251
END DESCRIPTION:
XS GIS Cut Line= 5
0.462579233724550.493041476736230.431420345810310.47013794160989
0.42403354048582 0.46470822423080.416646735161320.45927850685171
0.383607569528120.43499286184705
#Sta/Elev= 8
     856    36.1     917    32.7     972    30.9     986    25.1    1013    25.1
    1027      31    1095    33.2    1150    37.2
#Mann= 3 , 0 , 0
     856      .1       0     972     .04       0    1027      .1       0
Bank Sta=972,1027
XS Rating Curve= 0 ,0
Exp/Cntr=0.3,0.1

Type RM Length L Ch R = 1 ,20.238  ,57,57,57
BEGIN DESCRIPTION:
River mile 20.238 - Upstream end of culvert
END DESCRIPTION:
XS GIS Cut Line= 5
0.476400332507690.474238699546610.445241444593450.45133516442026
0.437854639268960.445905447041170.430467833944460.44047572966208
0.397428668311260.41619008465743
#Sta/Elev= 10
     856    36.1     917    32.7     972    30.9     986    25.1     993    25.1
    1007    25.1    1013    25.1    1027      31    1095    33.2    1150    37.2
#Mann= 3 , 1 , 0
     856      .4       0     972     .04       0    1027      .4       0
#XS Ineff= 2 , 0
             988    33.7    1012            33.7
Permanent Ineff=
       F       F
Bank Sta=972,1027
XS Rating Curve= 0 ,0
Exp/Cntr=0.5,0.3

Type RM Length L Ch R = 2 ,20.237  ,,,
BEGIN DESCRIPTION:
Twin Circular Pipe Crossing
END DESCRIPTION:
Bridge Culvert-0,0,1,-1, 0
Deck Dist Width WeirC Skew NumUp NumDn MinLoCord MaxHiCord MaxSubmerge Is_Ogee
10,40,2.6,0, 8, 8, 33.7, , 0.95, 0, 2,2,,
     856     917     972     993    1007    1027    1095    1150
    36.1    34.8    33.9    33.8    33.8    33.7    35.7    37.2
                                                                
     856     917     972     993    1007    1027    1095    1150
    36.1    34.8    33.9    33.8    33.8    33.7    35.7    37.2
                                                                
Multiple Barrel Culv=1,6,,50,0.013,0.5,1,1,1,25.1,25, 2,Culvert # 1 , 0 ,5
     996     996    1004    1004
Culvert Bottom n=0.013
BC Design=,, 0 ,, 0 ,,,,,,
BC HTab HWMax=37.2
BC Use User HTab Curves=0
BC User HTab FreeFlow(D)= 0

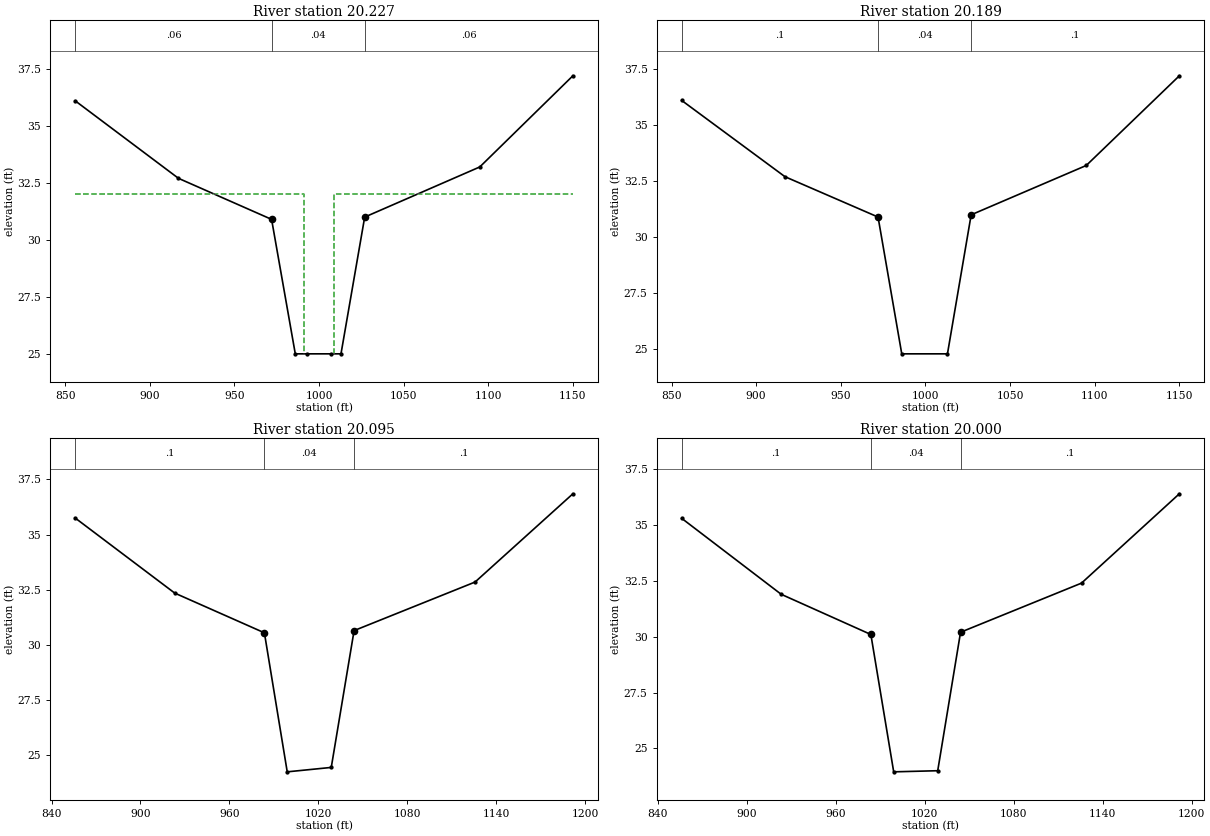
Type RM Length L Ch R = 1 ,20.227  ,100,100,100
BEGIN DESCRIPTION:
River mile 20.227 - Downstream end of culvert
END DESCRIPTION:
XS GIS Cut Line= 5
0.48765465580253 0.45892786669220.456495767888290.43602433156585
 0.44910896256380.43059461418676 0.44172215723930.42516489680767
 0.40868299160610.40087925180302
#Sta/Elev= 10
     856    36.1     917    32.7     972    30.9     986      25     993      25
    1007      25    1013      25    1027      31    1095    33.2    1150    37.2
#Mann= 3 , 1 , 0
     856     .06       0     972     .04       0    1027     .06       0
#XS Ineff= 2 , 0
             991      32    1009              32
Permanent Ineff=
       F       F
Bank Sta=972,1027
XS Rating Curve= 0 ,0
Exp/Cntr=0.5,0.3

Type RM Length L Ch R = 1 ,20.189  ,600,500,550
BEGIN DESCRIPTION:
River mile 20.189
END DESCRIPTION:
XS GIS Cut Line= 5
0.527143509468640.40520564615041 0.49598462155440.38230211102407
0.488597816229910.376872393644980.481211010905410.37144267626589
0.448171845272210.34715703126123
#Sta/Elev= 8
     856    36.1     917    32.7     972    30.9     986    24.8    1013    24.8
    1027      31    1095    33.2    1150    37.2
#Mann= 3 , 0 , 0
     856      .1       0     972     .04       0    1027      .1       0
Bank Sta=972,1027
XS Rating Curve= 0 ,0
Exp/Cntr=0.3,0.1

Type RM Length L Ch R = 1 ,20.095  ,500,500,450
BEGIN DESCRIPTION:
River mile 20.095
END DESCRIPTION:
XS GIS Cut Line= 5
 0.6226667160193 0.29513176551360.599196862093990.25965420066945
0.594432208218230.250766309516660.589667554342470.24187841836386
0.561806516541480.20132046527086
#Sta/Elev= 8
     856   35.75   923.1   32.35   983.6   30.55     999   24.25  1028.7   24.45
  1044.1   30.65  1125.7   32.85  1191.7   36.85
#Mann= 3 , 0 , 0
     856      .1       0   983.6     .04       0  1044.1      .1       0
Bank Sta=983.6,1044.1
XS Rating Curve= 0 ,0
Exp/Cntr=0.3,0.1

Type RM Length L Ch R = 1 ,20.000  ,0,0,0
BEGIN DESCRIPTION:
River mile 20.000 - Downstream Cross Section
END DESCRIPTION:
XS GIS Cut Line= 5
0.76620232637897 0.21839032484230.74610415387576 0.1808995911528
       0.7413395       0.17201170.73657484612424 0.1631238088472
0.713326489240370.11975678348643
#Sta/Elev= 8
     856    35.3   923.1    31.9   983.6    30.1     999   23.95  1028.7      24
  1044.1    30.2  1125.7    32.4  1191.7    36.4
#Mann= 3 , 0 , 0
     856      .1       0   983.6     .04       0  1044.1      .1       0
Bank Sta=983.6,1044.1
XS Rating Curve= 0 ,0
Exp/Cntr=0.3,0.1

Chan Stop Cuts=-1
Use User Specified Reach Order=0
Composite Channel Slope=5